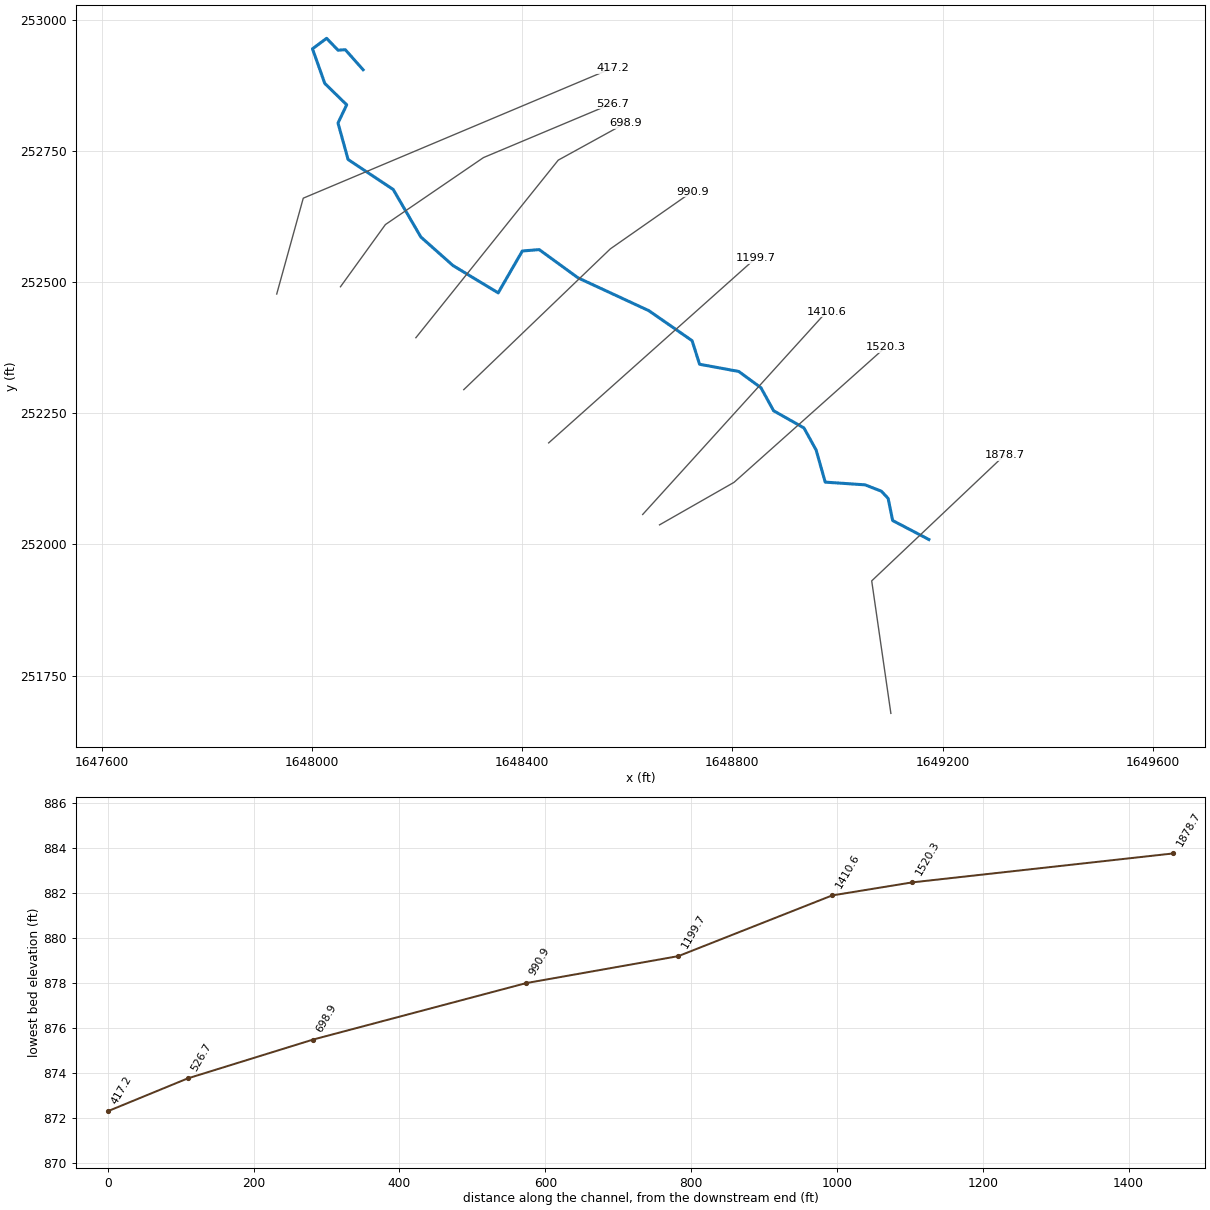
--- BEECHLICK.prj (project) ---

Proj Title=BEECHLICK
Current Plan=p01
Default Exp/Contr=0,0
English Units
Geom File=g01
Flow File=f01
Plan File=p01
BEGIN DESCRIPTION:
END DESCRIPTION:
DSS Export Rating Curves= 0
DSS Export Rating Curve Sorted= 0
DSS Export Volume Flow Curves= 0
DXF OffsetX= 0
DXF OffsetY= 0
DXF ScaleX= 0
DXF ScaleY= 0

--- BEECHLICK.p01 (plan) ---

Plan Title=Floodplain
Program Version=4.00
Geom File=g01
Flow File=f01
K Sum by GR=0
Std Step Tol=0.01
Critical Tol=0.01
Num of Std Step Trials=20
Max Error Tol=0.3
Flow Tol Ratio=0.001
Split Flow NTrial=30
Split Flow Tol=0.02
Split Flow Ratio=0.02
Log Output Level=0
Friction Slope Method=1
Unsteady Friction Slope Method=2
Unsteady Bridges Friction Slope Method=1
Global Log Level=0
CheckData=False
Run HTab=0
Run UNet=0
Run PostProcess=0
UNET Theta=0
UNET Theta Warmup=0
UNET ZTol=0
UNET ZSATol=0
UNET MxIter=0
UNET MaxInSteps=0
UNET DtIC=0
UNET DtMin=0
UNET MaxCRTS=0
UNET WFStab=0
UNET SFStab=0
UNET WFX=0
UNET SFX=0
UNET DSS MLevel=0
UNET DZMax Abort=0
UNET Convert EG Bridges=0
UNET Use Existing IB Tables=0
UNET Froude Limit=0
UNET Froude Power=0
Write IC File=0
Echo Input=False
Echo Output=False
Write Detailed=0

--- BEECHLICK.f01 (steady flow) ---

Flow Title=NFF Regression Equation
Program Version=4.10
Number of Profiles= 1
Profile Names=P100yr
River Rch & RM=BEECHLICK,Main            ,1878.7
945.7087
River Rch & RM=BEECHLICK,Main            ,526.7
996.0628
Boundary for River Rch & Prof#=BEECHLICK,Main            , 1
Up Type= 0
Dn Type= 3
Dn Slope=0.0136
DSS Import GetInterval= 0
DSS Import GetPeak= 0
DSS Import FillOption= 0

--- BEECHLICK.g01 (geometry) ---

Geom Title=USGS 10m DEM
Program Version=4.10

River Reach=BEECHLICK       ,Main
Reach XY= 30
     1649173.951      252009.265     1649105.057      252045.434
     1649096.445      252087.632     1649083.528       252101.41
     1649052.526      252113.467     1648976.744      252118.634
      1648959.52      252179.776     1648936.269      252221.973
     1648878.571      252254.698     1648854.458      252298.617
     1648812.261      252329.619     1648737.714      252343.362
     1648723.494      252388.296     1648641.029      252445.587
      1648506.48      252508.087     1648432.696      252561.907
     1648400.578      252559.303     1648354.571      252479.442
     1648268.633      252531.525     1648207.442      252585.967
     1648154.918       252676.49      1648068.98      252733.782
     1648049.883      252803.226     1648066.376      252837.948
      1648024.71      252878.747     1648001.272      252944.719
     1648028.182      252964.684     1648049.883      252942.115
     1648063.772      252942.983     1648097.626      252904.789

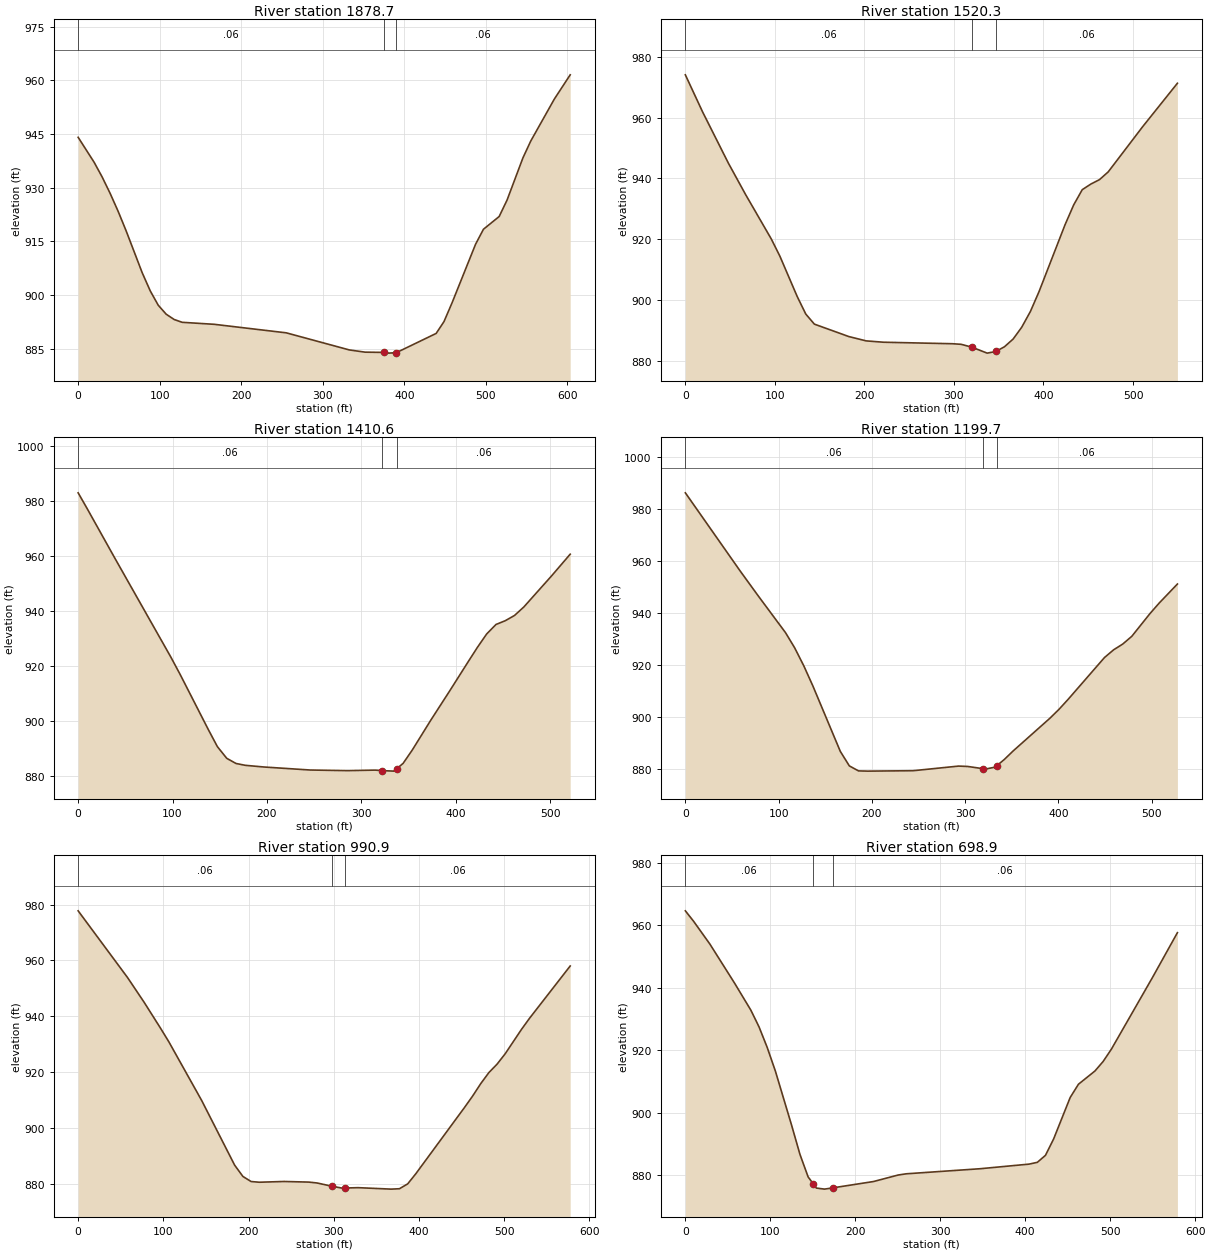
Type RM Length L Ch R = 1 ,1878.7  ,360.5,358.4,356.1
XS GIS Cut Line= 3
     1649101.664      251677.798     1649065.205      251930.402
     1649317.809      252169.986
#Sta/Elev= 30
       0  944.07    19.6  937.09    29.4     933    39.3  928.37    49.1  923.36
    58.9  917.91    78.5  906.26    88.4  901.17    98.2  897.16     108  894.64
   117.8  893.16   127.6  892.38   166.9  891.82   255.2  889.44   332.6  884.66
   351.9  884.04   375.2  883.97   380.9  883.77   390.2   883.9     439  889.27
   448.6  892.57   458.3   897.7   487.3  914.16     497  918.37   516.3  921.94
     526  926.54   545.4   938.3     555  943.01     584  954.77   603.4  961.52
#Mann= 3 , 0 , 0
       0     .06       0   375.2    .045       0   390.2     .06       0
Bank Sta=375.2,390.2
XS Rating Curve= 0 ,0
Exp/Cntr=0.3,0.1

Type RM Length L Ch R = 1 ,1520.3  ,106.4,109.7,112.3
XS GIS Cut Line= 3
     1648661.559      252037.173     1648803.293      252118.237
     1649091.247      252375.715
#Sta/Elev= 30
       0  974.05    19.2  961.88      48  945.02    67.2   934.7      96  920.03
   105.6  914.37   124.9  901.13   134.5  895.34   144.1  892.02   182.6  887.93
   201.9  886.51   221.2  886.07   298.5  885.57   308.1  885.38   320.3  884.41
   337.1  882.48   346.8  883.02   356.4  884.57   366.1  887.11   375.7     891
   385.4  896.18     395  902.69     424  924.66   433.7  931.22   443.3  936.26
     453  938.12   462.6  939.57   472.3  942.11   510.9  957.03   549.6  971.28
#Mann= 3 , 0 , 0
       0     .06       0   320.3    .045       0   346.8     .06       0
Bank Sta=320.3,346.8
XS Rating Curve= 0 ,0
Exp/Cntr=0.3,0.1

Type RM Length L Ch R = 1 ,1410.6  ,213.4,210.9,207.2
XS GIS Cut Line= 2
     1648629.503      252056.973     1648979.268      252443.423
#Sta/Elev= 30
       0  982.91     9.8  977.03    39.3  958.94    98.4  923.17   108.2  916.89
   137.7  897.11   147.5  890.78   157.4  886.55   167.2  884.68     177  884.01
   196.7   883.4   245.9   882.3   285.2  882.08   314.7  882.27   322.3  882.08
   334.4   881.9   337.3  882.73   344.2  884.71     354   889.6   373.7  900.48
   393.4  910.93     413  921.53   422.9  926.81   432.7  931.67   442.6  935.13
   452.4  936.49   462.2  938.39   472.1  941.48   501.6  952.81   521.2  960.64
#Mann= 3 , 0 , 0
       0     .06       0   322.3    .045       0   337.3     .06       0
Bank Sta=322.3,337.3
XS Rating Curve= 0 ,0
Exp/Cntr=0.3,0.1

Type RM Length L Ch R = 1 ,1199.7  ,207.4,208.7,208.7
XS GIS Cut Line= 2
     1648450.622      252193.423     1648843.851      252544.986
#Sta/Elev= 30
       0  986.16    58.6   956.2    78.1  946.56   107.4  932.41   117.2  926.58
     127  919.65   136.8  911.86   166.1   886.8   175.8  881.21   185.6  879.29
   195.4   879.2   244.2  879.36     293  881.14   302.8  880.99   318.7  880.16
   322.3  880.04   332.1  880.74   333.7  881.22   341.9  883.67   351.6  887.02
   390.7  899.49   400.5  902.93   410.3  906.77   449.3  922.85   459.1  925.82
   468.9  928.04   478.6  931.01   498.2   939.8   507.9  943.77   527.5  951.11
#Mann= 3 , 0 , 0
       0     .06       0   318.7    .045       0   333.7     .06       0
Bank Sta=318.7,333.7
XS Rating Curve= 0 ,0
Exp/Cntr=0.3,0.1

Type RM Length L Ch R = 1 ,990.9   ,290.7,292,295.3
XS GIS Cut Line= 3
     1648289.164      252294.986     1648567.809      252563.215
     1648724.059       252672.59
#Sta/Elev= 30
       0  977.74      58  953.82    77.4  944.99    96.7  935.67   106.4  930.83
     145  909.76   183.7  886.58   193.4  882.54     203  880.72   212.7  880.47
   241.7  880.74   270.7  880.52   280.4   880.2   297.7  879.05   309.4  878.38
   312.7   878.4   328.8  878.52   367.4     878   377.1  878.14   386.8  879.89
   396.3  883.51   453.5  907.28   463.1  911.41   472.6  915.85   482.1  919.78
   491.7   922.8   501.2  926.51   520.3  935.24   529.8  939.24   577.5  957.97
#Mann= 3 , 0 , 0
       0     .06       0   297.7    .045       0   312.7     .06       0
Bank Sta=297.7,312.7
XS Rating Curve= 0 ,0
Exp/Cntr=0.3,0.1

Type RM Length L Ch R = 1 ,698.9   ,178.7,172.2,165.2
XS GIS Cut Line= 3
     1648198.018      252393.944     1648468.851      252732.486
     1648596.455      252802.798
#Sta/Elev= 30
       0  964.65     9.6  961.34    28.9  953.99    57.8  941.54    77.1  932.83
    86.7  927.48    96.3  920.92     106  913.28   125.2  895.84   134.9  886.62
   144.5  879.41   150.4  877.23   154.2  875.83   163.8  875.49   173.4  875.89
   221.6  877.93   250.5  880.01   260.1   880.4   346.8  882.02   404.6   883.5
   414.3  884.07   423.9  886.32   433.5  891.57     453  904.86   462.7  909.09
   482.1  913.33   491.8   916.4   501.5  920.34   550.1  943.41   579.2  957.65
#Mann= 3 , 0 , 0
       0     .06       0   150.4    .045       0   173.4     .06       0
Bank Sta=150.4,173.4
XS Rating Curve= 0 ,0
Exp/Cntr=0.3,0.1

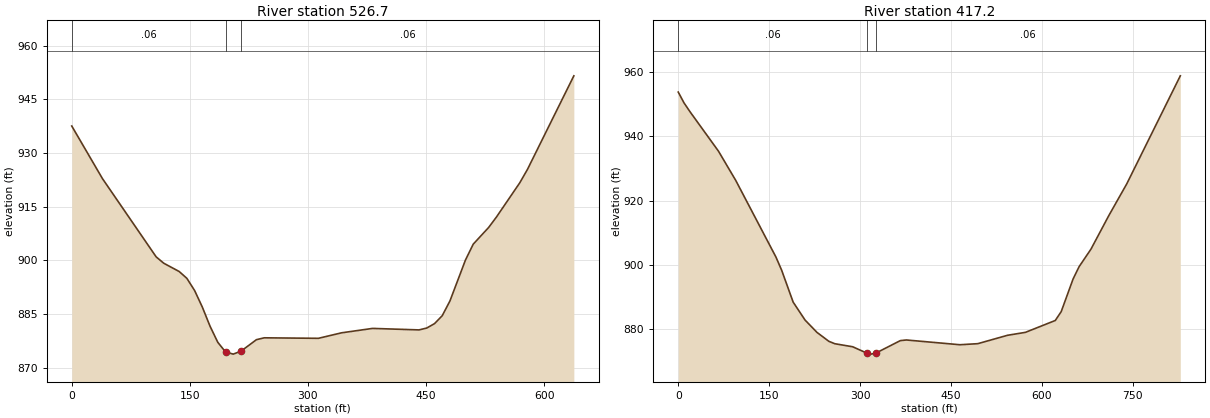
Type RM Length L Ch R = 1 ,526.7   ,115.6,109.6,104.3
XS GIS Cut Line= 4
     1648054.549      252491.061      1648140.02      252609.632
     1648326.562      252737.339     1648571.382      252840.355
#Sta/Elev= 30
       0  937.52      39  922.81   107.2  900.95   116.9  899.16   136.4  896.86
   146.2  894.95     156  891.56   165.8  886.94   175.6  881.59   185.5  877.06
   195.3  874.38   205.1  873.76     215  874.59   234.6   877.8   244.5  878.32
   313.3  878.18   342.8  879.72   382.1  880.95   441.1  880.53   450.9  881.05
   460.8  882.28   470.6   884.5   480.4  888.62   500.1  900.05     510   904.5
   529.6  909.17   539.5  912.09     569  921.61   578.8  925.36   637.8  951.55
#Mann= 3 , 0 , 0
       0     .06       0   195.3    .045       0     215     .06       0
Bank Sta=195.3,215
XS Rating Curve= 0 ,0
Exp/Cntr=0.3,0.1

Type RM Length L Ch R = 1 ,417.2   ,479.6,417.2,344.3
XS GIS Cut Line= 3
     1647933.276      252477.271      1647983.77      252659.979
     1648572.312      252908.243
#Sta/Elev= 30
       0  953.78     9.5  950.43      19  947.78    66.4   935.4    94.8  926.34
   161.1  902.52   170.6   898.4   189.6  888.47   209.2   882.9   228.9  879.06
   248.5  876.28   258.4  875.53   287.8  874.59   310.7  872.65   317.3   872.3
   325.7  872.59   366.4   876.5   376.3   876.7   464.7  875.22   494.2  875.55
   543.3  878.16   572.8  879.07     622  882.76   631.8  885.51   651.4  895.66
   661.3  899.48   680.9  904.94   710.4  915.39   739.9  925.22   828.3  958.83
#Mann= 3 , 0 , 0
       0     .06       0   310.7    .045       0   325.7     .06       0
Bank Sta=310.7,325.7
XS Rating Curve= 0 ,0
Exp/Cntr=0.3,0.1

Chan Stop Cuts=-1
Use User Specified Reach Order=0
Composite Channel Slope=5